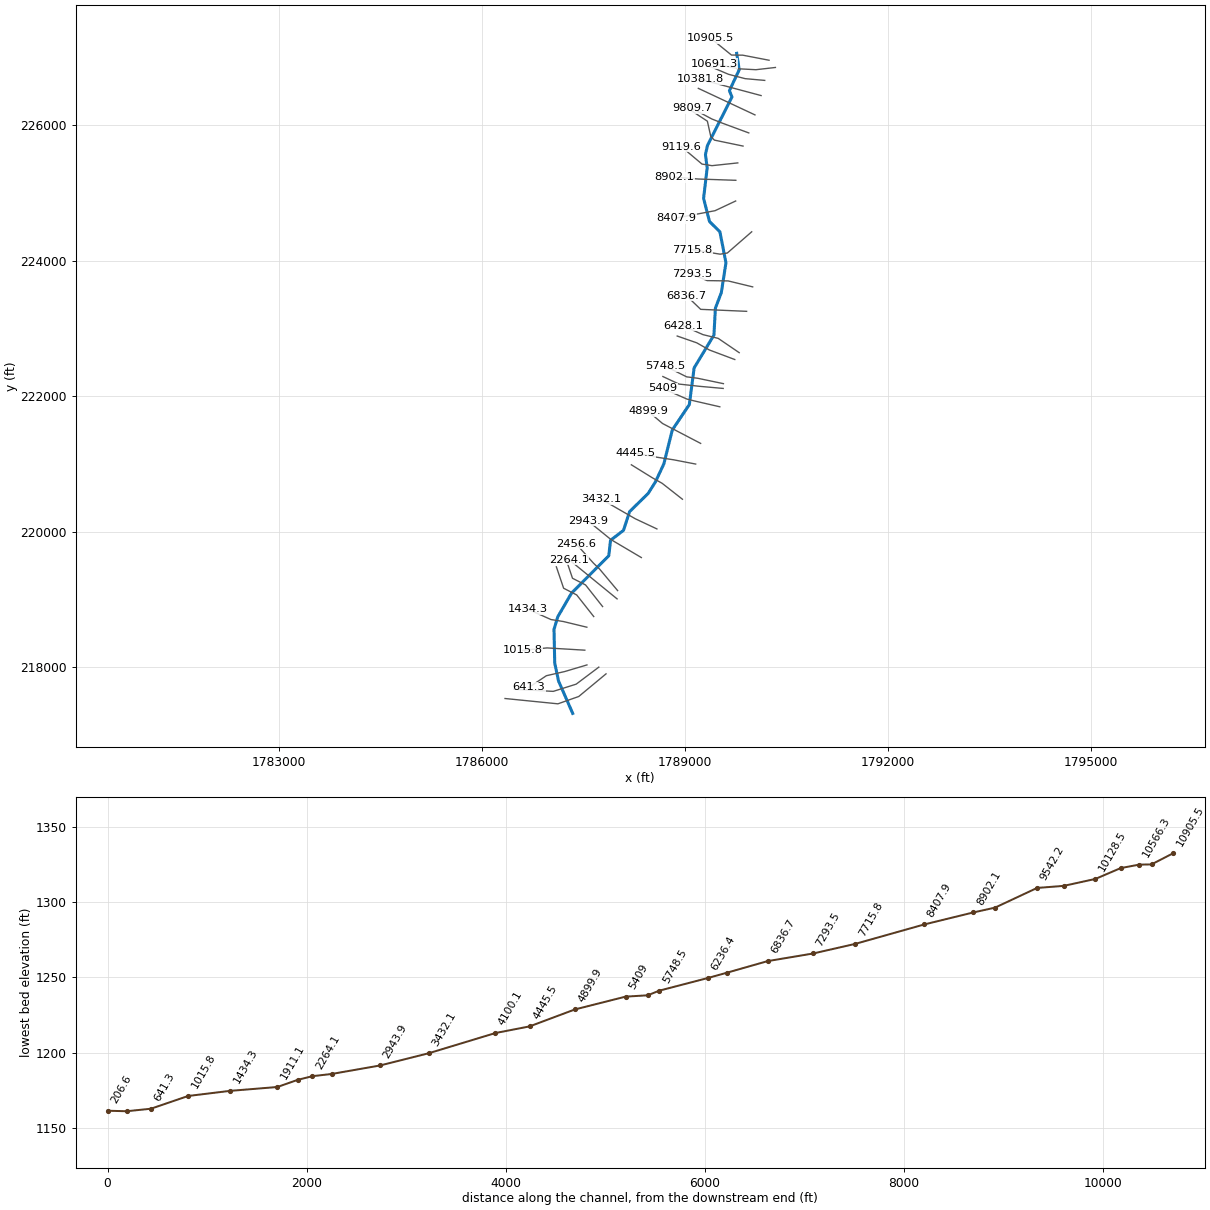
--- ShanonMlCr.prj (project) ---

Proj Title=ShanonMlCr
Current Plan=p01
Default Exp/Contr=0,0
English Units
Geom File=g01
Flow File=f01
Plan File=p01
BEGIN DESCRIPTION:
END DESCRIPTION:
DSS Export Rating Curves= 0
DSS Export Rating Curve Sorted= 0
DSS Export Volume Flow Curves= 0
DXF OffsetX= 0
DXF OffsetY= 0
DXF ScaleX= 0
DXF ScaleY= 0

--- ShanonMlCr.p01 (plan) ---

Plan Title=Floodplain
Program Version=4.00
Geom File=g01
Flow File=f01
K Sum by GR=0
Std Step Tol=0.01
Critical Tol=0.01
Num of Std Step Trials=20
Max Error Tol=0.3
Flow Tol Ratio=0.001
Split Flow NTrial=30
Split Flow Tol=0.02
Split Flow Ratio=0.02
Log Output Level=0
Friction Slope Method=1
Unsteady Friction Slope Method=2
Unsteady Bridges Friction Slope Method=1
Global Log Level=0
CheckData=False
Run HTab=0
Run UNet=0
Run PostProcess=0
UNET Theta=0
UNET Theta Warmup=0
UNET ZTol=0
UNET ZSATol=0
UNET MxIter=0
UNET MaxInSteps=0
UNET DtIC=0
UNET DtMin=0
UNET MaxCRTS=0
UNET WFStab=0
UNET SFStab=0
UNET WFX=0
UNET SFX=0
UNET DSS MLevel=0
UNET DZMax Abort=0
UNET Convert EG Bridges=0
UNET Use Existing IB Tables=0
UNET Froude Limit=0
UNET Froude Power=0
Write IC File=0
Echo Input=False
Echo Output=False
Write Detailed=0

--- ShanonMlCr.f01 (steady flow) ---

Flow Title=NFF Regression Equation
Program Version=4.00
Number of Profiles=1
Profile Names=P100yr
River Rch & RM=ShanonMlCr,Main      ,10905.5
709.5392
River Rch & RM=ShanonMlCr,Main      ,9809.7
753.6412
River Rch & RM=ShanonMlCr,Main      ,9542.2
828.3786
River Rch & RM=ShanonMlCr,Main      ,7715.8
875.3118
River Rch & RM=ShanonMlCr,Main      ,4899.9
956.4219
River Rch & RM=ShanonMlCr,Main      ,206.6
1044.221
Boundary for River Rch & Prof#=ShanonMlCr,Main      ,1
Up Type=0
Dn Type=3
Dn Slope=0.009755

--- ShanonMlCr.g01 (geometry) ---

Geom Title=USGS 10m DEM
Program Version=4.00

River Reach=ShanonMlCr      ,Main
Reach XY= 30
     1789769.632      227064.607     1789806.845      226822.136
     1789661.602      226513.565     1789699.466      226420.315
     1789337.207      225703.708     1789307.819      225570.333
     1789333.251      225374.792     1789280.127      224922.673
     1789367.725      224581.324     1789521.445      224429.864
     1789610.738       223971.53      1789541.79      223530.714
     1789454.758      223301.829     1789432.865      222904.107
     1789140.535      222420.198     1789069.487      221878.621
     1788818.013      221503.694     1788693.139      221002.993
      1788566.91      220733.797     1788460.781      220566.295
     1788186.566      220297.502     1788096.468      220021.434
     1787905.122      219874.207     1787879.344      219646.503
     1787328.671      219094.302     1787125.783      218745.606
     1787069.788      218558.376     1787080.571      218061.212
     1787136.521      217797.288     1787345.841      217318.914

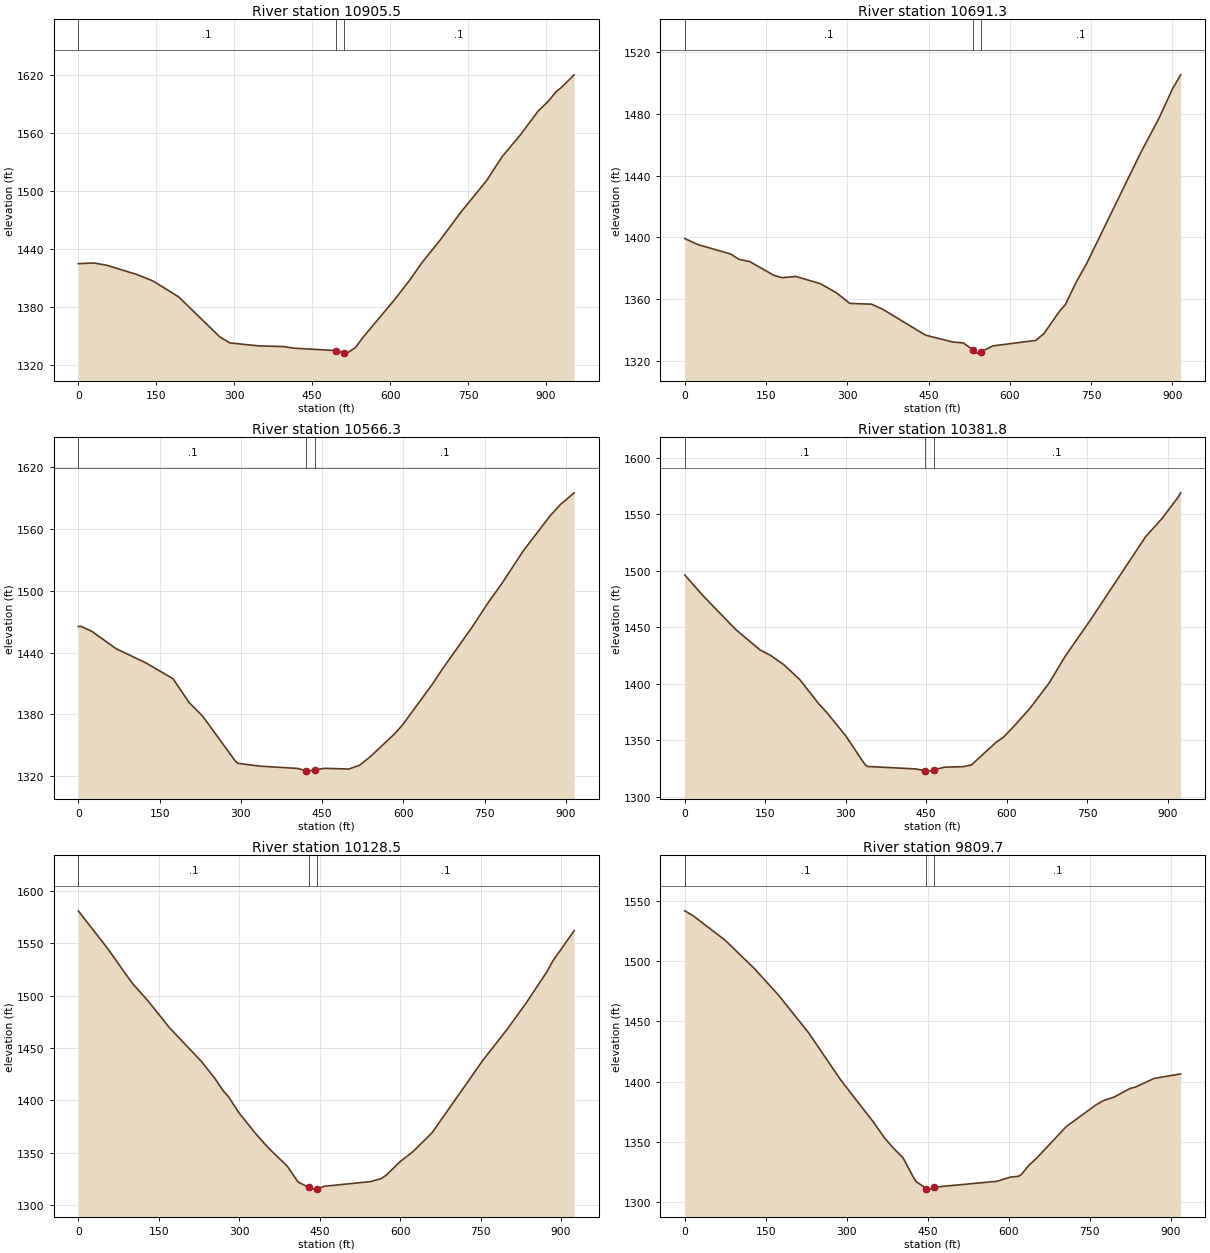
Type RM Length L Ch R = 1 ,10905.5 ,218.8,214.2,211
XS GIS Cut Line= 4
     1790247.462      226962.968     1789858.991      227037.723
     1789691.788       227039.56     1789387.828      227286.345
#Sta/Elev= 30
       0 1424.77    29.7 1425.49    54.4 1423.22   113.7 1413.41   143.4 1406.96
   192.8 1390.61     272 1349.26   291.8 1342.89   346.2 1339.89   395.6  1339.1
   415.3 1337.43   495.6 1334.99   510.6 1332.73   513.6 1332.35   518.6 1332.87
   533.3 1338.03   548.1 1348.81   607.4 1386.77   637.2 1407.34   661.9 1426.19
   696.6 1449.32   736.3 1477.98   785.8 1510.64   815.6 1535.32   850.3 1557.51
     885 1582.47   904.8 1592.74   919.6 1602.44   929.6 1606.82   954.3  1619.9
#Mann= 3 , 0 , 0
       0      .1       0   495.6    .045       0   510.6      .1       0
Bank Sta=495.6,510.6
XS Rating Curve= 0 ,0
Exp/Cntr=0.3,0.1

Type RM Length L Ch R = 1 ,10691.3 ,129.8,125,123.2
XS GIS Cut Line= 4
     1790341.644      226856.252     1790053.928       226823.13
       1789799.8       226836.34     1789435.757      226909.411
#Sta/Elev= 30
       0 1399.18      25 1395.21    84.9 1389.18    99.9 1385.74   119.8  1384.3
   164.8 1375.34   179.8 1373.86   204.7 1374.67   249.7 1370.09   279.6 1364.21
   304.6 1357.21   344.5 1356.75   364.5 1353.62   444.3  1336.7   494.2 1332.25
   514.2 1331.63   532.4 1327.14   539.1 1325.04   547.4 1325.95   568.8 1329.73
     648 1333.27   662.9  1337.6   692.6 1352.56   702.5 1356.37   722.3  1370.8
   742.1 1383.17   841.1 1454.37   875.8 1477.32   900.5 1496.21   915.4 1505.18
#Mann= 3 , 0 , 0
       0      .1       0   532.4    .045       0   547.4      .1       0
Bank Sta=532.4,547.4
XS Rating Curve= 0 ,0
Exp/Cntr=0.3,0.1

Type RM Length L Ch R = 1 ,10566.3 ,184.7,184.5,184.3
XS GIS Cut Line= 4
      1790183.41      226665.203     1789894.938      226690.926
     1789648.727      226755.235     1789306.971       226900.39
#Sta/Elev= 30
       0 1465.39       5 1465.53      25 1460.64    69.9 1443.78   124.8 1430.01
   174.8 1414.69   204.7 1391.41   229.7 1378.16   289.6 1334.83   294.6 1332.46
   334.5 1329.75   404.4 1327.52   421.2 1325.28   424.3 1324.88   436.2    1326
   454.3 1327.61   499.2 1326.91   519.1 1330.53   539.1 1338.96   583.7 1361.01
   598.6  1369.8     653 1408.88   672.8 1424.55   727.3 1465.02     757 1488.86
   781.7 1506.96   821.3 1538.72   870.8 1572.77   890.6 1584.14   915.4 1595.23
#Mann= 3 , 0 , 0
       0      .1       0   421.2    .045       0   436.2      .1       0
Bank Sta=421.2,436.2
XS Rating Curve= 0 ,0
Exp/Cntr=0.3,0.1

Type RM Length L Ch R = 1 ,10381.8 ,257.8,253.4,248.9
XS GIS Cut Line= 2
     1790130.164      226441.211     1789237.189      226680.073
#Sta/Elev= 30
       0 1496.32      35  1477.5    94.9 1448.07   139.9 1430.12   159.9 1425.12
   184.9 1416.76   214.8 1403.48   249.8  1382.2   264.8 1374.51   299.8 1354.02
   334.8 1329.23   339.8 1326.75   429.7 1324.57   448.7 1322.99   454.7 1322.59
   463.7 1323.73   484.7 1326.08   519.6 1326.58   534.6 1328.11   579.6 1347.84
   594.6 1352.84   614.6 1362.84   644.6 1378.83   679.5 1400.84   709.5  1424.6
   754.5 1455.24   859.4 1530.44   889.4 1546.16   919.4 1565.06   924.4 1569.13
#Mann= 3 , 0 , 0
       0      .1       0   448.7    .045       0   463.7      .1       0
Bank Sta=448.7,463.7
XS Rating Curve= 0 ,0
Exp/Cntr=0.3,0.1

Type RM Length L Ch R = 1 ,10128.5 ,317.4,318.8,320.1
XS GIS Cut Line= 2
     1790039.553      226155.697     1789202.487      226547.845
#Sta/Elev= 30
       0 1580.86      55 1544.68    99.9 1512.22   129.9 1494.97   169.9 1469.41
   229.8    1437   254.8 1420.87   269.8 1409.44   279.8 1403.72   299.8 1388.02
   329.8 1368.78   354.8 1354.47   389.7 1337.22   409.7 1322.19   429.3 1317.15
   439.7  1315.4   444.3 1315.79   459.7 1318.19   544.6 1322.57   564.6 1325.44
   574.6 1328.93   599.6 1341.52   624.6 1351.49   659.6 1369.24   754.5 1438.48
   799.4 1467.79   834.4 1492.54   874.4 1523.36   884.4 1532.89   924.4 1561.94
#Mann= 3 , 0 , 0
       0      .1       0   429.3    .045       0   444.3      .1       0
Bank Sta=429.3,444.3
XS Rating Curve= 0 ,0
Exp/Cntr=0.3,0.1

Type RM Length L Ch R = 1 ,9809.7  ,276.7,267.6,258.4
XS GIS Cut Line= 4
     1789947.949      225889.701     1789554.746      226034.855
     1789402.242      226095.489     1789106.421      226253.506
#Sta/Elev= 30
       0 1541.82      15 1537.88    74.8 1517.41   129.7 1493.53   174.6 1471.33
   229.5  1440.5   289.4 1401.06   349.3 1366.54   369.2 1353.81   384.2 1345.86
   404.2 1336.87   424.1 1320.14   429.1 1316.85   447.5 1311.28     454 1310.77
   462.5 1312.41   578.3 1317.26     603 1320.69   617.8 1321.43   622.7 1322.54
   637.5 1330.55   652.3 1336.72   706.6 1362.63   760.8  1380.4   775.6 1384.29
   795.3 1387.17   824.9 1394.34   834.8 1395.46   869.3 1402.68   918.6 1406.41
#Mann= 3 , 0 , 0
       0      .1       0   447.5    .045       0   462.5      .1       0
Bank Sta=447.5,462.5
XS Rating Curve= 0 ,0
Exp/Cntr=0.3,0.1

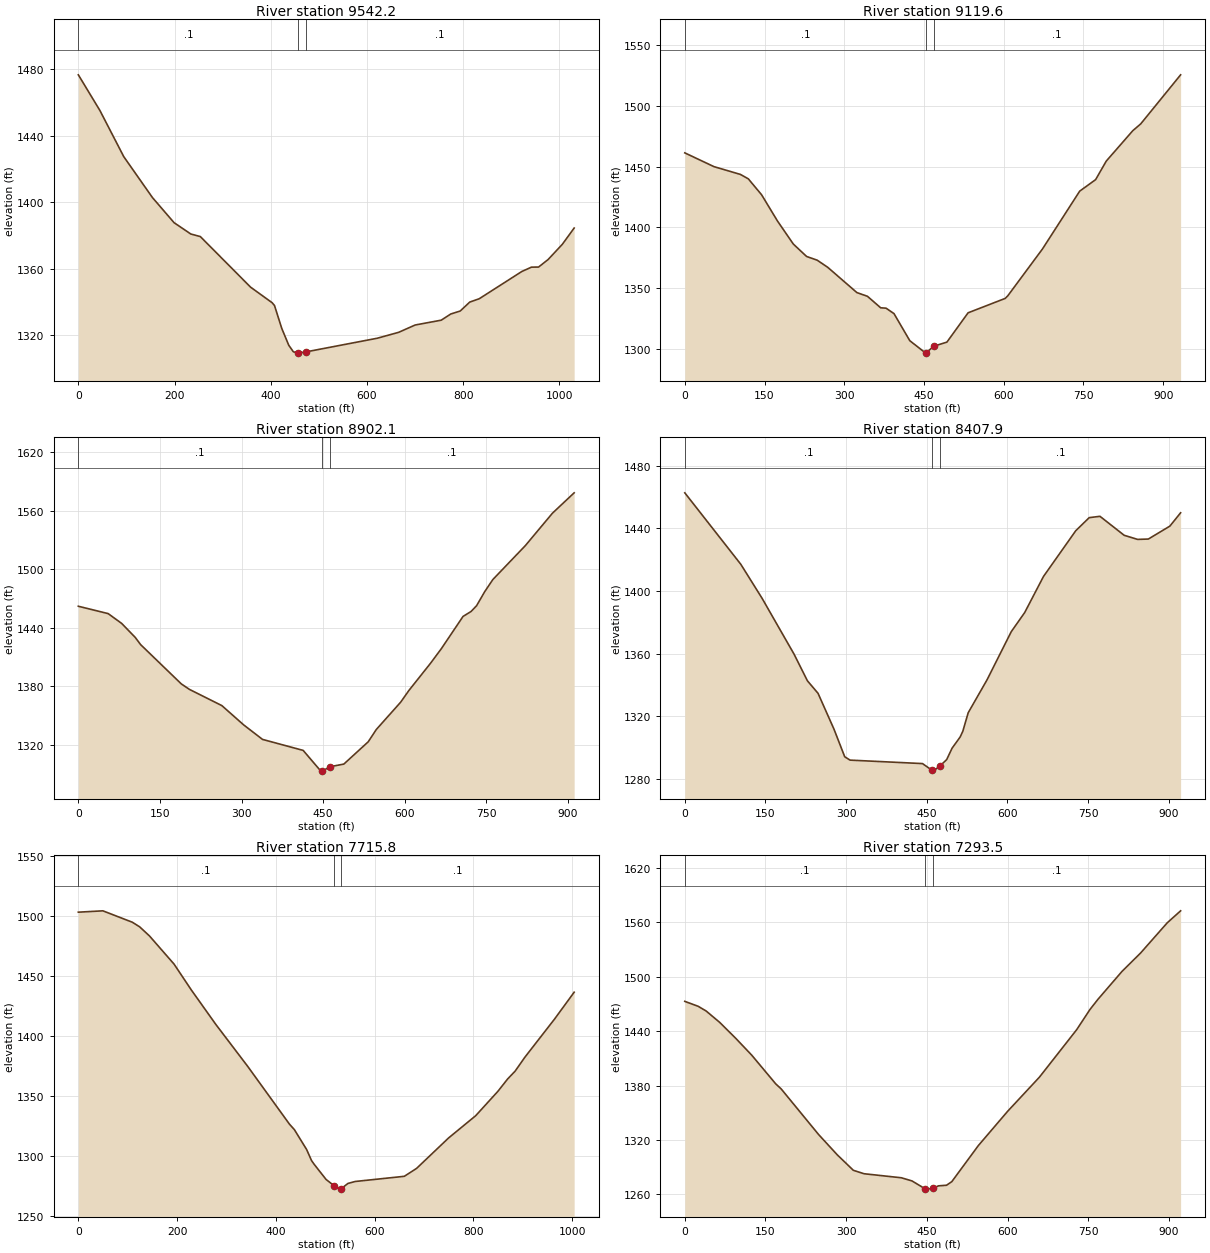
Type RM Length L Ch R = 1 ,9542.2  ,408.5,422.6,436.6
XS GIS Cut Line= 5
     1789863.537      225695.559     1789439.748      225783.456
     1789386.382      225836.822     1789336.155      226062.842
     1789092.869      226222.941
#Sta/Elev= 30
       0 1476.46    44.8 1455.09    94.5 1427.33   154.2 1402.75     199 1387.73
   233.8 1380.92   253.7 1379.36   358.2    1349     403 1339.66   407.9 1337.99
   422.9 1324.33   437.5 1314.16     447 1310.24   456.4  1309.4   457.7 1309.48
   472.7 1310.11   621.6 1318.34   665.9 1321.87   700.4 1326.28   754.6 1329.18
   774.4 1332.88   794.1 1334.68   813.9 1340.04   833.6 1342.04   922.4 1358.44
   942.2 1361.01     957 1361.07   976.8 1365.57  1006.4 1374.72    1031 1384.49
#Mann= 3 , 0 , 0
       0      .1       0   457.7    .045       0   472.7      .1       0
Bank Sta=457.7,472.7
XS Rating Curve= 0 ,0
Exp/Cntr=0.3,0.1

Type RM Length L Ch R = 1 ,9119.6  ,214.7,217.5,220.3
XS GIS Cut Line= 4
     1789785.638      225447.024     1789404.228      225406.215
     1789256.686      225429.759     1788950.616      225687.172
#Sta/Elev= 30
       0 1461.33    54.8    1450   104.6 1443.58   119.6  1439.9   144.5 1426.81
   174.4 1405.17   204.2 1386.19   229.2 1375.95   249.1  1372.9     269    1367
   323.8  1346.2   343.7 1343.13   368.6 1333.65   378.6 1333.37   393.6 1328.87
   423.4 1306.53   453.3 1296.31   453.5 1296.36   468.5    1302   493.2 1305.39
     533 1329.53     603 1341.42     608 1343.71     673 1382.16     743 1429.78
     773 1439.29     793 1454.57   842.9 1479.59   857.9 1485.26   932.9 1525.64
#Mann= 3 , 0 , 0
       0      .1       0   453.5    .045       0   468.5      .1       0
Bank Sta=453.5,468.5
XS Rating Curve= 0 ,0
Exp/Cntr=0.3,0.1

Type RM Length L Ch R = 1 ,8902.1  ,489.2,494.2,499.2
XS GIS Cut Line= 3
      1789756.58      225190.077     1789204.309      225208.986
     1788846.812        225236.9
#Sta/Elev= 30
       0 1462.08    54.8 1454.54    79.6 1444.51   104.5  1430.2   114.5 1422.76
   189.2 1382.53   204.1  1376.9   263.8 1360.25   303.7 1340.57   338.5 1325.63
   413.2 1314.36   443.1 1294.83     448 1293.13     448 1293.12     463 1297.69
   487.9 1300.32   532.7 1323.14   547.6 1335.76   592.4  1363.8   607.4  1375.7
   647.2 1403.62   667.1 1418.57     707 1451.64   721.9 1456.78   731.9 1462.64
   746.8 1476.99   761.8 1489.46   821.5 1524.21   871.3 1557.43   911.2 1578.31
#Mann= 3 , 0 , 0
       0      .1       0     448    .045       0     463      .1       0
Bank Sta=448,463
XS Rating Curve= 0 ,0
Exp/Cntr=0.3,0.1

Type RM Length L Ch R = 1 ,8407.9  ,692.6,692.1,691.7
XS GIS Cut Line= 3
     1789754.188      224884.526     1789449.165      224741.248
     1788874.248      224633.116
#Sta/Elev= 30
       0 1462.64   104.1 1417.08   143.7 1395.37   203.2 1359.72     228 1342.74
   247.8 1334.74   277.5 1311.82   297.4 1294.28   307.3 1292.14     442 1289.93
   459.6  1285.7     462 1285.12   474.6 1288.46     487 1292.48     497 1299.74
     512 1306.87     517 1310.56     527 1322.36     562 1343.34     607 1374.04
     632 1386.25     667 1409.29     727 1438.46     752  1446.8     772 1447.66
     817 1435.56     842 1432.93     862 1433.16     902  1441.4     922 1449.91
#Mann= 3 , 0 , 0
       0      .1       0   459.6    .045       0   474.6      .1       0
Bank Sta=459.6,474.6
XS Rating Curve= 0 ,0
Exp/Cntr=0.3,0.1

Type RM Length L Ch R = 1 ,7715.8  ,427.1,422.3,417.4
XS GIS Cut Line= 4
     1789991.279      224429.851     1789631.238      224116.551
     1789524.506      224099.286     1789111.028      224166.137
#Sta/Elev= 30
       0 1503.34    49.7 1504.47   109.4 1494.95   124.3 1491.08   144.2 1483.46
   193.9    1460   228.7 1438.51   278.4 1409.72     343 1374.69   427.6 1326.45
   437.5 1321.91   462.4 1305.26   472.3 1296.07   477.3 1293.14   501.8 1280.29
   517.4 1275.24   531.3 1272.23   532.4  1272.6   546.1 1276.98   560.8 1278.61
   660.2 1282.92   685.1 1289.54   749.9 1314.93   804.8 1333.51   849.7 1353.82
   869.6 1364.21   884.6 1370.66   904.5 1382.36   964.4  1414.1  1004.2 1436.55
#Mann= 3 , 0 , 0
       0      .1       0   517.4    .045       0   532.4      .1       0
Bank Sta=517.4,532.4
XS Rating Curve= 0 ,0
Exp/Cntr=0.3,0.1

Type RM Length L Ch R = 1 ,7293.5  ,457.9,456.8,455.8
XS GIS Cut Line= 4
     1790005.724      223616.474     1789643.149      223704.371
      1789332.37       223709.08     1789112.628      223800.116
#Sta/Elev= 30
       0 1472.85    24.9  1467.4    39.8 1462.16    64.7 1449.78    94.5 1432.24
   124.4 1413.57   169.1 1381.86   179.1 1376.39   248.7 1326.08   283.5 1303.65
   313.4 1286.58   333.3 1282.82   402.7 1278.36   422.4 1274.88   447.2 1266.05
     452 1265.85   462.2 1267.12   471.8 1269.48   486.6 1270.12   496.4  1274.1
   545.8 1313.89     600 1351.52   659.2 1389.22   728.5 1441.57   753.3 1463.93
   768.1  1475.1   812.7 1505.79   847.4 1526.17     897  1559.5   921.8 1572.66
#Mann= 3 , 0 , 0
       0      .1       0   447.2    .045       0   462.2      .1       0
Bank Sta=447.2,462.2
XS Rating Curve= 0 ,0
Exp/Cntr=0.3,0.1

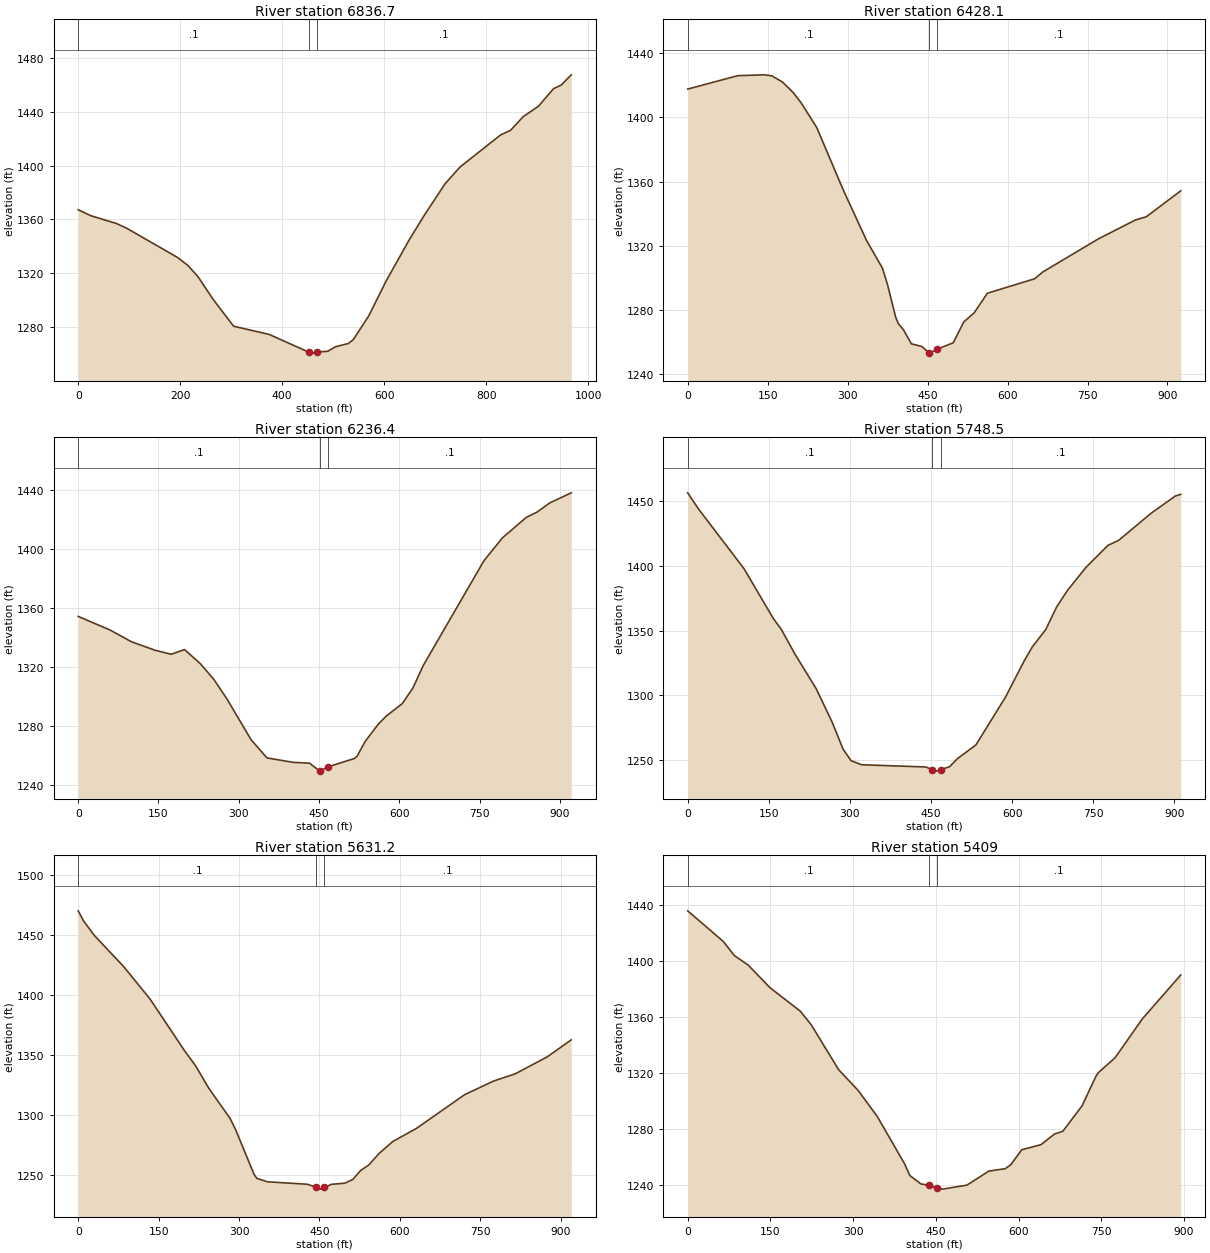
Type RM Length L Ch R = 1 ,6836.7  ,413,408.5,404.1
XS GIS Cut Line= 3
     1789915.971      223255.272     1789237.271      223284.669
     1789029.994      223483.734
#Sta/Elev= 30
       0 1367.23      25 1362.76    74.9 1357.04    94.9 1353.54   194.8 1331.81
   214.8 1325.98   234.8 1317.62   264.7 1300.62   304.7 1280.77   374.6 1274.66
   453.4 1261.29   459.6 1260.79   468.4 1261.59   489.5 1262.19   504.5 1265.54
   529.5 1267.91   539.5 1270.86   569.4 1288.25   604.4 1314.77   649.4 1345.13
   679.3 1363.54     719 1386.34   748.7 1398.97     828  1422.7   847.8 1426.22
   872.6 1436.37   902.3 1444.04     932  1457.1   946.9 1459.75   966.7 1467.38
#Mann= 3 , 0 , 0
       0      .1       0   453.4    .045       0   468.4      .1       0
Bank Sta=453.4,468.4
XS Rating Curve= 0 ,0
Exp/Cntr=0.3,0.1

Type RM Length L Ch R = 1 ,6428.1  ,198.1,191.7,185.4
XS GIS Cut Line= 4
     1789806.392      222644.933     1789496.253      222856.171
     1789271.802      222911.107     1788980.462      223040.062
#Sta/Elev= 30
       0  1417.6    93.8 1425.96   143.2 1426.49     158 1425.87   177.8 1421.99
   197.5 1415.57   212.3 1409.29   241.9 1393.76   291.3 1355.12   335.7 1323.15
   365.4 1305.97   375.2 1295.35     390 1275.66   394.9 1271.56   404.7  1267.7
   419.5 1258.92   439.2 1257.24     453 1253.25   453.9  1253.1     468 1255.57
   498.2 1259.55   517.8 1272.49   537.5 1278.25   562.1 1290.41   651.1 1299.46
   666.1 1303.67   770.6 1324.33   840.3 1336.11   860.2 1338.04   924.9 1354.23
#Mann= 3 , 0 , 0
       0      .1       0     453    .045       0     468      .1       0
Bank Sta=453,468
XS Rating Curve= 0 ,0
Exp/Cntr=0.3,0.1

Type RM Length L Ch R = 1 ,6236.4  ,479.1,487.9,496.8
XS GIS Cut Line= 4
     1789741.109      222543.823     1789364.408      222685.086
     1789179.196      222790.248     1788890.392      222890.702
#Sta/Elev= 30
       0 1354.23    59.6 1345.01    99.3  1337.1     144 1331.29   173.8 1328.61
   198.7 1331.78   228.5 1322.13   253.3 1311.67   278.2 1298.24   322.8  1270.9
   352.6 1258.51   402.3 1255.45     432 1254.97   450.8  1249.8   451.8 1249.56
   465.8 1252.35   516.2 1258.13   521.2 1259.74     536 1269.58   560.8  1281.4
   575.7 1286.87   605.4  1295.2   625.2 1305.72   644.9 1321.19   758.3 1392.04
   792.8 1407.43   837.2 1421.22     857 1424.74   881.6 1431.11   921.1 1437.81
#Mann= 3 , 0 , 0
       0      .1       0   450.8    .045       0   465.8      .1       0
Bank Sta=450.8,465.8
XS Rating Curve= 0 ,0
Exp/Cntr=0.3,0.1

Type RM Length L Ch R = 1 ,5748.5  ,116.9,117.3,117.7
XS GIS Cut Line= 4
     1789573.163      222187.526     1789190.183      222267.575
     1789030.085      222287.979     1788708.319      222448.078
#Sta/Elev= 30
       0 1456.68    19.8 1444.28     104 1398.02   158.5 1359.29   173.3 1350.83
   198.1    1332   237.7 1304.97   267.4 1278.88   287.2 1258.33   302.1 1249.24
   321.9 1246.09   440.2 1244.38   452.7 1242.31   459.7 1241.16   467.7 1242.27
   484.2 1244.54   498.8 1250.77   533.1 1261.46   587.6 1298.32   622.5  1326.6
   637.5  1337.4   662.5 1350.96   682.4 1368.31   702.4 1381.11   737.3 1399.26
   777.3 1415.99   797.2 1419.89   857.1 1440.85   902.1 1454.23     912 1455.53
#Mann= 3 , 0 , 0
       0      .1       0   452.7    .045       0   467.7      .1       0
Bank Sta=452.7,467.7
XS Rating Curve= 0 ,0
Exp/Cntr=0.3,0.1

Type RM Length L Ch R = 1 ,5631.2  ,225.2,222.2,219.2
XS GIS Cut Line= 4
     1789570.024      222116.894     1789218.436      222148.286
     1788917.075      222181.247     1788678.497      222292.688
#Sta/Elev= 30
       0    1470     9.9 1461.67    29.8 1449.64    84.5 1423.69   134.2 1396.38
   198.9 1353.04   218.8 1340.98   243.6 1322.13   283.4 1296.89   293.3 1287.94
   328.1 1250.24   333.1 1247.05     353 1244.17   427.5 1242.11   444.3 1239.55
   452.4 1238.06   459.3 1239.42   472.3 1242.07   497.1    1243     512 1246.06
   526.9 1253.65   541.8 1258.13   561.7 1268.02   586.6 1277.72   631.3 1288.82
   720.7  1316.8   775.4 1328.26   815.1 1334.16   874.8 1348.32   919.5 1362.47
#Mann= 3 , 0 , 0
       0      .1       0   444.3    .045       0   459.3      .1       0
Bank Sta=444.3,459.3
XS Rating Curve= 0 ,0
Exp/Cntr=0.3,0.1

Type RM Length L Ch R = 1 ,5409    ,514.5,509.1,503.7
XS GIS Cut Line= 4
      1789520.01      221845.847     1789151.157      221930.605
     1789036.577      221958.857     1788672.432      222118.955
#Sta/Elev= 30
       0 1435.84    64.7 1413.92    84.7 1403.86   109.6 1397.15   149.4 1380.92
   204.2 1364.22   224.1 1354.47   273.9 1322.36   308.8 1307.79   343.6 1289.19
   393.2 1255.36     403 1246.85   422.7 1240.95     438 1239.77     453 1238.11
   462.1 1237.17   506.4 1240.02   546.2 1250.03     576 1251.77     586 1254.61
   605.9 1265.27   640.7 1268.91   665.5 1276.56   680.4 1278.44   715.3 1296.64
   740.1 1317.48   745.1 1320.44   774.9 1330.84   824.6 1358.67   894.3 1390.09
#Mann= 3 , 0 , 0
       0      .1       0     438    .045       0     453      .1       0
Bank Sta=438,453
XS Rating Curve= 0 ,0
Exp/Cntr=0.3,0.1

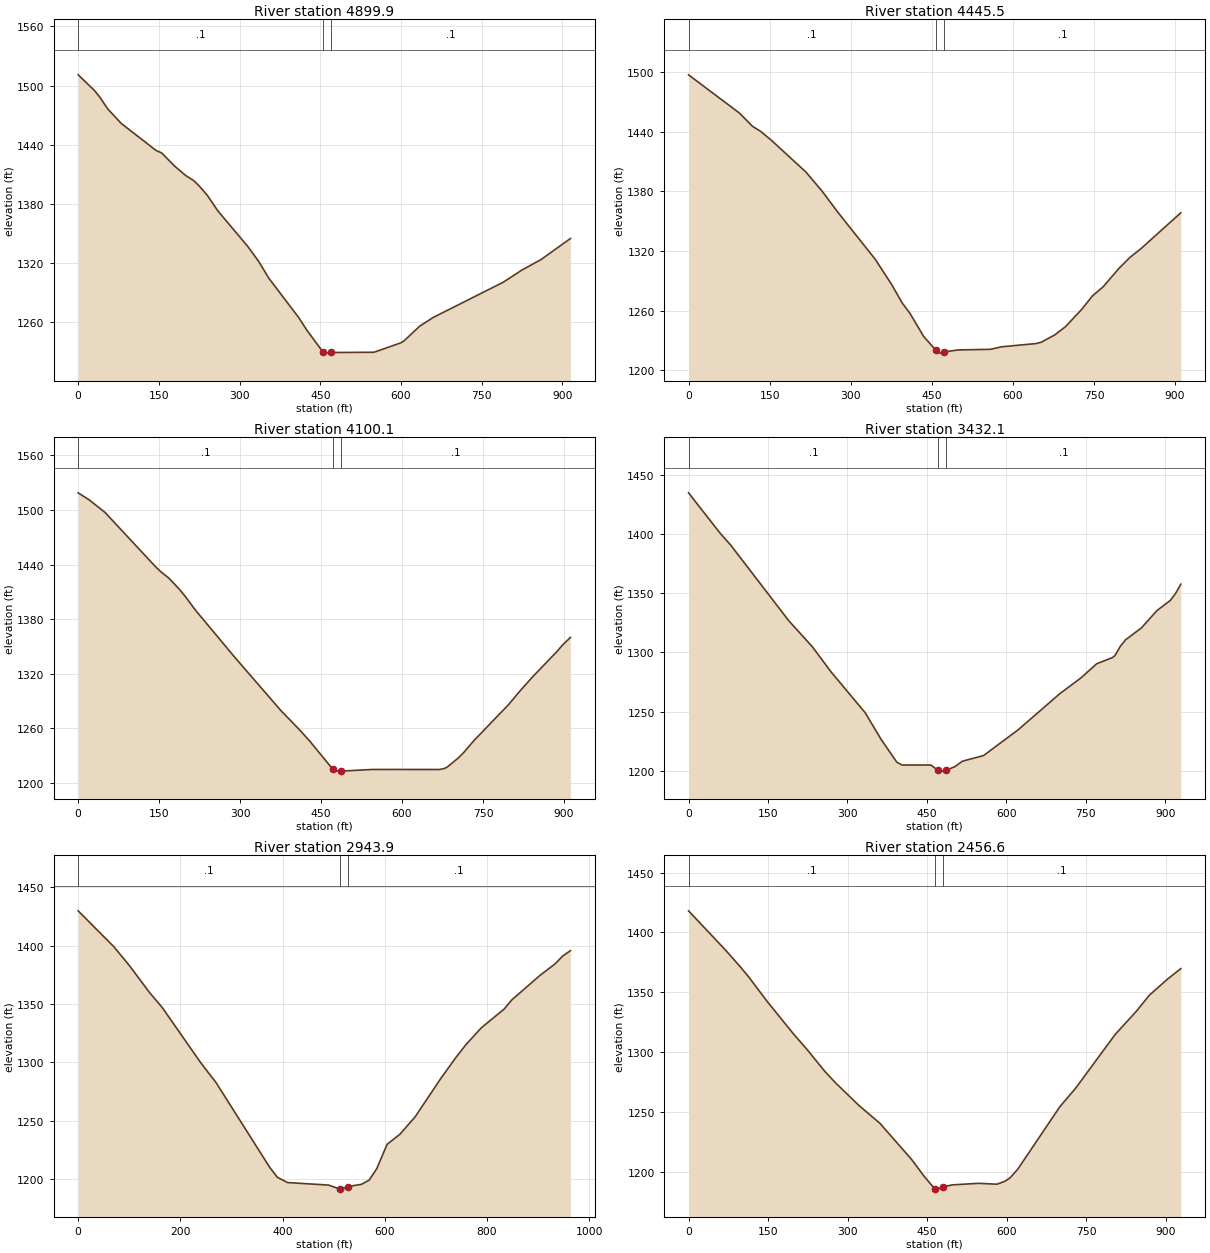
Type RM Length L Ch R = 1 ,4899.9  ,447.1,454.4,461.8
XS GIS Cut Line= 3
     1789236.625      221305.322     1788673.788       221598.93
     1788460.127      221779.822
#Sta/Elev= 30
       0 1510.97      30 1495.27      40 1488.54      55 1476.38      80 1461.72
     145 1434.17     155  1431.8     180 1418.04   199.9 1408.82   214.9 1403.62
   224.9 1398.26   239.9 1388.82   259.9 1372.77   314.9 1337.12   334.9 1322.21
   354.9 1304.24   409.9 1264.74   424.9 1252.02   454.6 1230.08   459.9 1228.66
   469.6  1229.3   549.8 1229.54   599.8 1239.13   604.8 1240.71   634.8 1256.05
   659.8 1264.85   789.8 1300.54   824.8 1312.97   859.8 1323.44   914.8 1344.92
#Mann= 3 , 0 , 0
       0      .1       0   454.6    .045       0   469.6      .1       0
Bank Sta=454.6,469.6
XS Rating Curve= 0 ,0
Exp/Cntr=0.3,0.1

Type RM Length L Ch R = 1 ,4445.5  ,353.4,345.3,337.2
XS GIS Cut Line= 4
     1789163.478      221000.197     1788833.886        221063.7
      1788589.03       221101.37     1788267.544      221162.455
#Sta/Elev= 30
       0 1497.27    93.8 1458.97   118.5 1445.45   133.3 1440.43     153 1431.58
   217.2 1399.49   246.8 1380.45   276.4 1358.95   345.6 1311.62   375.3 1286.76
   395.1 1267.98     410 1257.06   434.8 1234.34   457.5 1220.25   464.5 1217.41
   472.5 1218.62   499.2 1220.63   558.6 1221.25   578.4 1223.72   642.9 1227.04
   652.8 1228.46   677.6 1235.78   697.4 1244.07   727.2 1261.35     747 1274.84
   766.8 1284.04   796.6 1302.87   816.4 1313.66   836.3 1322.16   910.6 1358.55
#Mann= 3 , 0 , 0
       0      .1       0   457.5    .045       0   472.5      .1       0
Bank Sta=457.5,472.5
XS Rating Curve= 0 ,0
Exp/Cntr=0.3,0.1

Type RM Length L Ch R = 1 ,4100.1  ,668.3,668.1,667.8
XS GIS Cut Line= 4
      1788967.67      220480.743     1788668.431      220715.526
     1788528.737      220794.006     1788212.904      220989.276
#Sta/Elev= 30
       0 1518.78    19.8 1511.32    49.4 1497.47   143.2  1437.7   153.1  1432.1
     168 1425.06   187.7 1412.69   197.6 1405.61   217.3 1389.86   291.4 1337.17
   375.4 1279.65   409.5 1258.74   428.9 1246.04   471.9 1214.96   477.5  1213.1
   486.9 1212.97   487.2 1212.96   545.5  1214.8   669.3 1214.74   679.2 1216.01
   684.2 1217.66     704 1227.34   713.9 1233.18   733.7 1246.86     798 1286.47
   817.8 1300.62   842.6 1317.04   887.2 1344.55     897 1351.34   911.9 1359.88
#Mann= 3 , 0 , 0
       0      .1       0   471.9    .045       0   486.9      .1       0
Bank Sta=471.9,486.9
XS Rating Curve= 0 ,0
Exp/Cntr=0.3,0.1

Type RM Length L Ch R = 1 ,3432.1  ,489,488.2,484.1
XS GIS Cut Line= 3
     1788590.387      220042.432     1788270.404      220192.577
     1787771.051      220479.576
#Sta/Elev= 30
       0 1435.14    59.7 1400.93    79.6 1390.89   189.2  1326.9     234  1304.7
   268.8 1283.72   333.6 1248.97   363.4 1226.56   393.2 1207.14   403.1 1204.73
   457.7 1204.72     471 1200.16   477.6 1199.56     486 1200.22   502.4 1203.25
   517.3 1207.99     557 1212.74   621.6 1234.27     701 1265.13   740.7 1278.41
   770.5 1290.42   800.3 1295.67   805.3  1297.5   815.2 1305.17   825.1 1310.72
   854.9 1320.74   884.7  1335.6   909.6 1344.03   919.5 1349.93   929.4 1357.78
#Mann= 3 , 0 , 0
       0      .1       0     471    .045       0     486      .1       0
Bank Sta=471,486
XS Rating Curve= 0 ,0
Exp/Cntr=0.3,0.1

Type RM Length L Ch R = 1 ,2943.9  ,492.5,487.3,485.4
XS GIS Cut Line= 3
     1788360.599      219619.472     1787913.114      219884.057
     1787568.664      220163.513
#Sta/Elev= 30
       0 1429.83      70 1399.03     100  1383.1     140 1359.68     165 1346.73
   239.9 1299.71   269.9 1282.67   374.9 1210.11   389.9 1201.57   409.9 1197.07
   489.9 1194.92   512.4 1191.47   514.9 1191.44   527.4 1193.64   554.7 1195.56
   569.7 1199.21   584.6 1209.12   604.6 1229.81   629.5 1238.37   659.4  1253.3
   709.2 1285.89   739.1 1304.11   759.1 1315.29     789 1329.61   833.8 1345.71
   848.8 1353.58   903.6 1374.43   933.5 1384.44   948.5 1391.18   963.4  1395.7
#Mann= 3 , 0 , 0
       0      .1       0   512.4    .045       0   527.4      .1       0
Bank Sta=512.4,527.4
XS Rating Curve= 0 ,0
Exp/Cntr=0.3,0.1

Type RM Length L Ch R = 1 ,2456.6  ,190.7,192.5,194.2
XS GIS Cut Line= 4
      1788009.75      219131.973     1787743.021      219450.161
     1787651.985      219538.058     1787393.255      219825.271
#Sta/Elev= 30
       0 1418.09    69.2 1385.59    98.9  1370.7   113.7 1362.78   148.3 1342.44
   197.7 1315.44   222.4  1302.9     257 1284.12   276.8  1274.7   321.3 1255.64
   360.8 1240.76   420.1 1210.85   444.4 1196.46     459 1188.77   465.5 1186.22
   468.7 1185.78   480.5 1187.79   497.9 1189.33   546.7 1190.62   581.4 1189.88
   596.3 1192.26   606.2 1195.11     621 1202.52   700.3 1254.61   730.1 1270.08
   804.4 1314.82     844    1334   868.8 1347.55   903.5 1361.18   928.3 1369.88
#Mann= 3 , 0 , 0
       0      .1       0   465.5    .045       0   480.5      .1       0
Bank Sta=465.5,480.5
XS Rating Curve= 0 ,0
Exp/Cntr=0.3,0.1

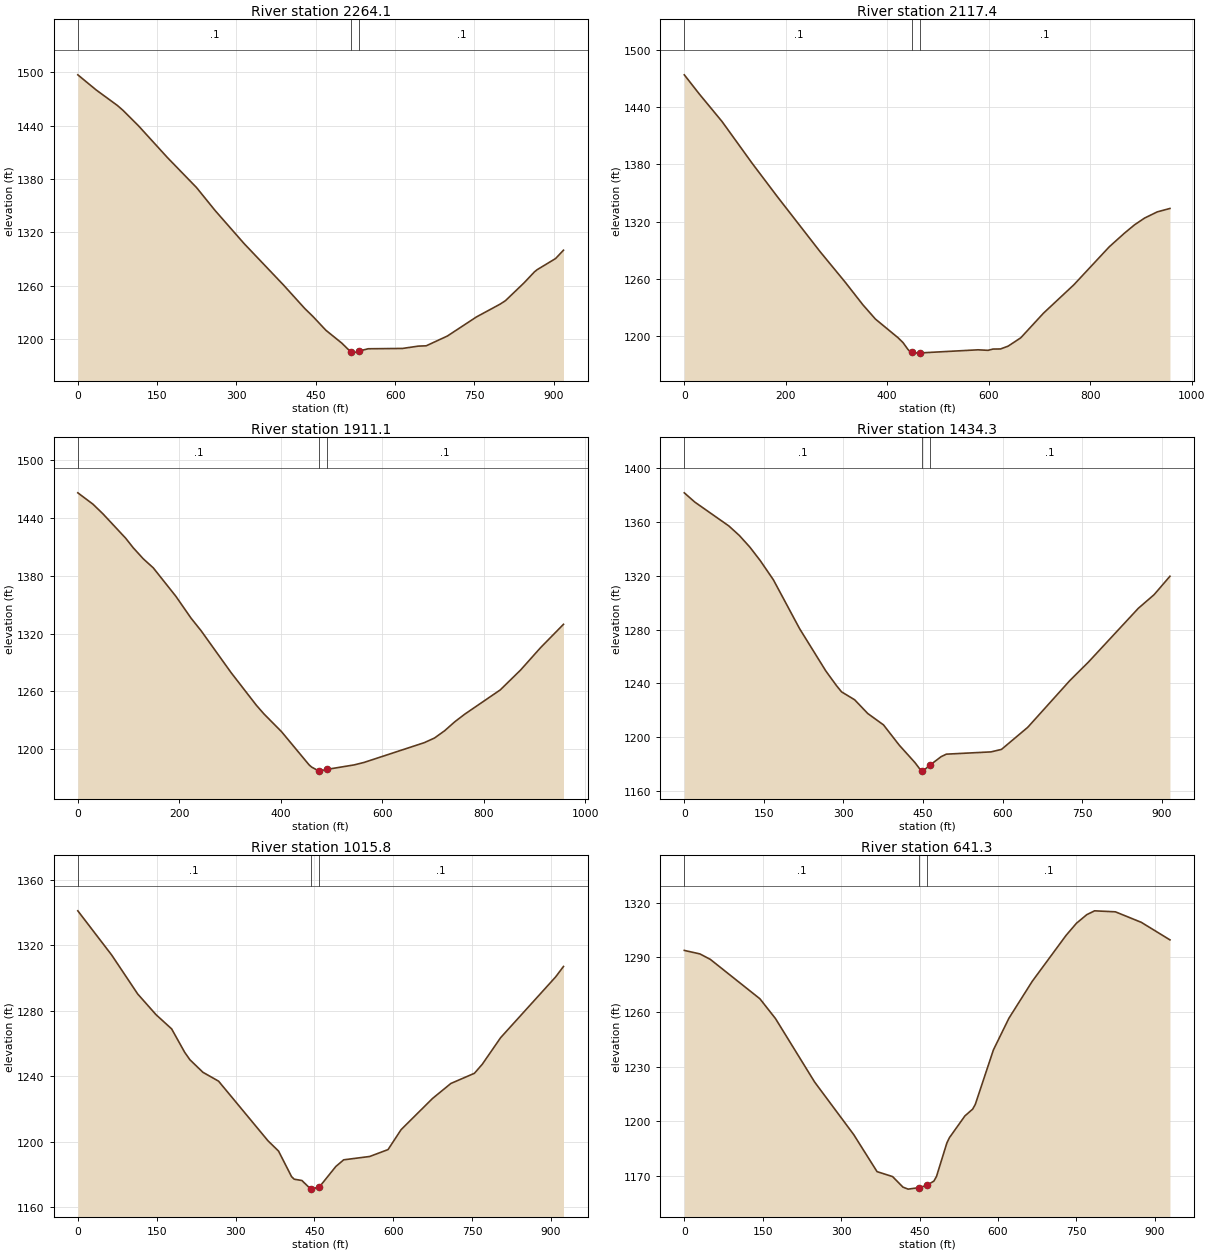
Type RM Length L Ch R = 1 ,2264.1  ,141.8,146.7,151.6
XS GIS Cut Line= 2
      1788002.07      219009.329     1787290.342      219589.933
#Sta/Elev= 30
       0 1497.19    34.9  1480.1    74.9 1462.71    84.9 1457.56   114.8 1439.84
   169.7 1404.02   224.6 1370.39   259.6 1344.68   314.5 1307.46   389.4 1260.64
   429.3 1234.42   444.3 1225.77   469.2    1210   499.2  1195.6   517.2 1185.12
   519.2 1184.32   532.2 1186.68   549.1 1189.22     614 1189.58     644  1192.2
   658.9 1192.55   698.9 1203.53   753.8 1224.97   798.7  1239.4   808.7 1243.26
   843.6 1263.11   863.6 1275.68   868.6  1278.1   903.5 1290.62   918.5 1300.02
#Mann= 3 , 0 , 0
       0      .1       0   517.2    .045       0   532.2      .1       0
Bank Sta=517.2,532.2
XS Rating Curve= 0 ,0
Exp/Cntr=0.3,0.1

Type RM Length L Ch R = 1 ,2117.4  ,206.3,206.4,206.4
XS GIS Cut Line= 4
     1787787.873      218896.046     1787536.109      219215.098
     1787343.049      219313.982     1787235.784      219630.115
#Sta/Elev= 30
       0 1473.92    29.7 1453.74    74.4 1424.93   133.8 1381.07   183.4 1346.09
   267.6 1288.42   317.2 1256.33   351.9 1232.69   376.7 1217.65   421.2 1198.12
   431.1 1192.96   440.9 1185.74   445.9 1183.09   449.4 1182.58   460.6 1181.91
   464.4 1182.11     579 1185.39   598.7 1184.85   608.5 1186.18   623.3 1186.28
   638.3 1189.24   663.2    1198     708 1223.85   767.8 1253.61   837.6 1293.47
   867.5 1307.76   887.4 1316.52   907.3 1323.65   932.2 1330.12   957.2  1333.7
#Mann= 3 , 0 , 0
       0      .1       0   449.4    .045       0   464.4      .1       0
Bank Sta=449.4,464.4
XS Rating Curve= 0 ,0
Exp/Cntr=0.3,0.1

Type RM Length L Ch R = 1 ,1911.1  ,470,476.7,483.5
XS GIS Cut Line= 4
     1787656.723      218748.754     1787404.959      219067.806
     1787211.899      219166.691     1787104.634      219482.823
#Sta/Elev= 30
       0 1466.13    29.7  1454.4    49.6 1444.27    94.2 1419.06     109 1409.19
   128.9 1397.66   148.7 1388.21   193.3 1358.65     223 1336.09   242.9 1322.96
   302.3 1279.26   351.9 1245.53   366.8 1236.55   401.5 1218.09   455.7  1183.7
   460.6  1181.4   475.4 1177.12   475.5 1177.13   490.5 1178.89   544.5 1183.57
   564.2 1186.16   683.1 1206.72     703 1211.51     723 1219.07   742.9 1228.34
   762.8 1236.34   832.6 1261.47   872.5 1282.01   912.3 1305.48   957.2 1329.58
#Mann= 3 , 0 , 0
       0      .1       0   475.5    .045       0   490.5      .1       0
Bank Sta=475.5,490.5
XS Rating Curve= 0 ,0
Exp/Cntr=0.3,0.1

Type RM Length L Ch R = 1 ,1434.3  ,416.3,418.5,420.8
XS GIS Cut Line= 4
     1787555.231      218591.194     1787209.361      218674.784
     1787024.149      218704.606     1786684.629      218857.032
#Sta/Elev= 30
       0 1381.83    19.8 1374.94      84 1357.16   103.8 1350.06   123.6  1341.4
   143.3 1331.29     168 1317.02   217.4 1280.64   266.9 1249.11   286.6  1238.4
   296.5 1233.58   321.2 1227.68   345.9 1217.46   375.6 1208.96   405.2 1193.91
   434.8 1180.94   444.7 1175.77   448.5 1174.82   449.6 1174.54   463.5 1179.11
   484.2 1185.31   494.1 1187.18   578.2 1188.87     598 1190.72   647.6 1207.21
     727 1242.05   761.8 1255.72     856 1295.82   885.8    1306   915.6 1319.69
#Mann= 3 , 0 , 0
       0      .1       0   448.5    .045       0   463.5      .1       0
Bank Sta=448.5,463.5
XS Rating Curve= 0 ,0
Exp/Cntr=0.3,0.1

Type RM Length L Ch R = 1 ,1015.8  ,367.9,374.5,381
XS GIS Cut Line= 3
      1787525.39         218252.     1786966.075      218285.526
     1786604.194       218249.19
#Sta/Elev= 30
       0 1340.91    64.5 1313.91     114 1290.16   148.8 1277.57   178.5 1268.89
   203.3 1254.63   213.2  1250.1     238 1242.43   267.8 1237.01     362 1200.57
   381.8 1194.41   406.6 1178.82   411.6 1177.23   426.4  1176.4     443 1171.24
   446.3 1171.16     458 1172.54   461.2 1173.13   490.9 1184.98   505.8 1189.03
   555.4 1191.08   590.2 1195.28   615.1 1207.45   674.9 1226.47   709.8 1235.62
   754.6 1241.82   769.6 1247.36   804.4 1263.53   909.1 1300.61     924 1306.97
#Mann= 3 , 0 , 0
       0      .1       0     443    .045       0     458      .1       0
Bank Sta=443,458
XS Rating Curve= 0 ,0
Exp/Cntr=0.3,0.1

Type RM Length L Ch R = 1 ,641.3   ,240.8,242.7,244.5
XS GIS Cut Line= 4
      1787556.63      218034.319     1787226.981      217936.267
     1786957.012      217875.053     1786701.117      217703.792
#Sta/Elev= 30
       0 1293.78    29.9 1291.86    49.8 1288.86   144.6 1267.22   174.4 1256.35
   249.2 1221.52     324 1192.63   368.6  1172.3   398.3 1169.58   418.1  1163.8
     428 1162.69   448.3 1163.47   463.3  1164.7   477.4 1167.13   482.3 1169.68
   502.1 1188.02     507 1190.94   536.7 1202.92   551.5 1206.64   556.5 1209.23
   591.1 1239.13   620.7  1256.5   665.4 1276.82     730 1302.02   749.9 1308.69
   769.7 1313.42   784.6 1315.52   824.4 1314.97     874 1309.19   928.7 1299.57
#Mann= 3 , 0 , 0
       0      .1       0   448.3    .045       0   463.3      .1       0
Bank Sta=448.3,463.3
XS Rating Curve= 0 ,0
Exp/Cntr=0.3,0.1

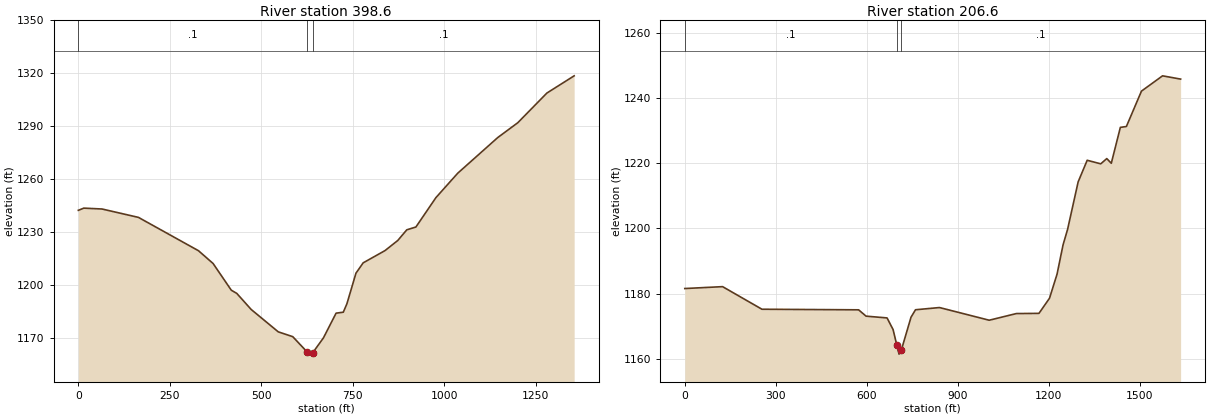
Type RM Length L Ch R = 1 ,398.6   ,191.3,192,192.8
XS GIS Cut Line= 4
     1787731.933      218001.632     1787397.611      217750.498
     1787058.579      217643.766     1786477.831      217675.158
#Sta/Elev= 30
       0 1242.46    14.9  1243.7    64.7 1243.21   164.3 1238.46   328.5 1219.57
   368.4 1212.33   418.1 1197.22     433 1195.43   472.4 1186.32   546.5 1173.63
     586 1170.92   625.2 1162.28   635.4 1161.02   640.2 1161.66   669.9 1170.21
   704.5 1184.22   724.2 1184.77   734.1 1189.54   758.8 1206.85   778.5 1212.71
   838.2 1219.65     873 1225.36   897.8 1231.42   922.7 1233.01   977.4 1249.66
    1037 1263.48  1146.4 1283.68  1201.1 1292.06  1280.6 1308.86  1355.2 1318.63
#Mann= 3 , 0 , 0
       0      .1       0   625.2    .045       0   640.2      .1       0
Bank Sta=625.2,640.2
XS Rating Curve= 0 ,0
Exp/Cntr=0.3,0.1

Type RM Length L Ch R = 1 ,206.6   ,203.4,206.6,209.8
XS GIS Cut Line= 4
     1787838.766      217902.546     1787435.382      217568.223
     1787127.742      217459.922     1786346.087      217538.401
#Sta/Elev= 30
       0 1181.53   124.7 1182.11   254.5 1175.16   573.3 1174.98     598 1173.03
   667.2 1172.49     687 1168.93   699.5 1164.09   706.8 1161.35   714.5 1162.65
   746.3 1172.72   761.1    1175   840.2 1175.68  1004.2 1171.78  1093.7 1173.83
  1168.3 1173.89  1203.1 1178.55  1227.9 1185.93  1247.8 1194.97  1262.8 1199.76
  1297.6 1214.35  1327.4 1220.99  1372.1 1219.89    1392 1221.51  1406.9 1220.07
  1436.8 1231.11  1456.7 1231.38  1506.4 1242.26    1576 1246.97  1635.6 1245.96
#Mann= 3 , 0 , 0
       0      .1       0   699.5    .045       0   714.5      .1       0
Bank Sta=699.5,714.5
XS Rating Curve= 0 ,0
Exp/Cntr=0.3,0.1

Chan Stop Cuts=-1
Use User Specified Reach Order=0